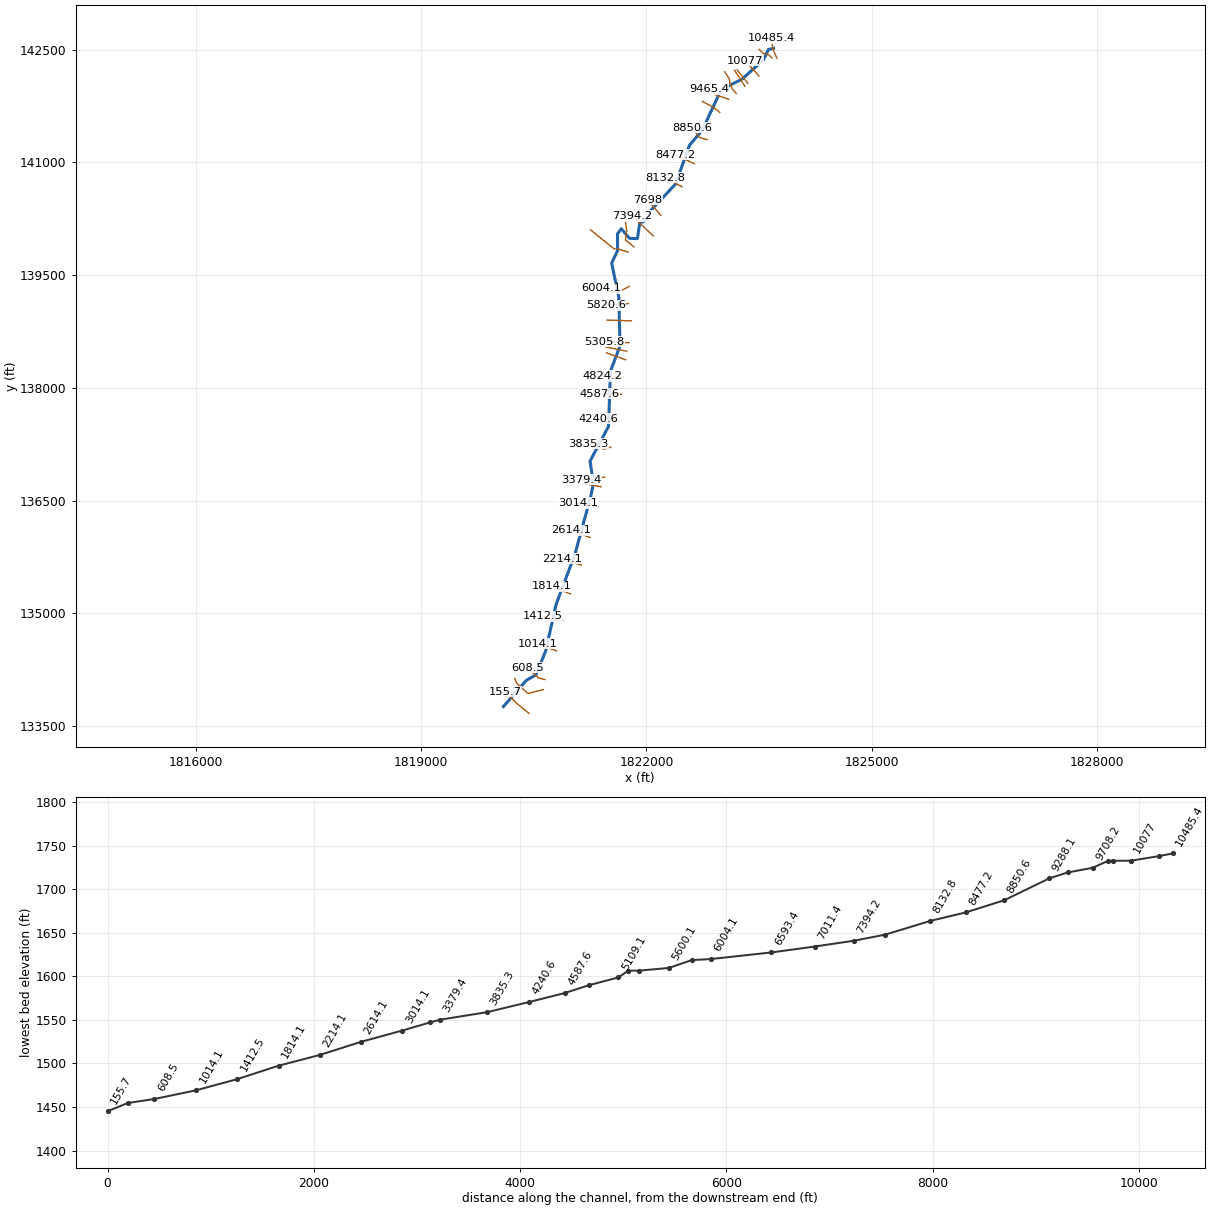
--- Harmon Branch A.prj (project) ---

Proj Title=Harmon Branch A
Current Plan=p01
Default Exp/Contr=0,0
English Units
Geom File=g01
Flow File=f01
Plan File=p01
BEGIN DESCRIPTION:
END DESCRIPTION:
DSS Export Rating Curves= 0
DSS Export Rating Curve Sorted= 0
DSS Export Volume Flow Curves= 0
DXF OffsetX= 0
DXF OffsetY= 0
DXF ScaleX= 0
DXF ScaleY= 0

--- Harmon Branch A.p01 (plan) ---

Plan Title=Floodplain
Program Version=4.00
Geom File=g01
Flow File=f01
K Sum by GR=0
Std Step Tol=0.01
Critical Tol=0.01
Num of Std Step Trials=20
Max Error Tol=0.3
Flow Tol Ratio=0.001
Split Flow NTrial=30
Split Flow Tol=0.02
Split Flow Ratio=0.02
Log Output Level=0
Friction Slope Method=1
Unsteady Friction Slope Method=2
Unsteady Bridges Friction Slope Method=1
Global Log Level=0
CheckData=False
Run HTab=0
Run UNet=0
Run PostProcess=0
UNET Theta=0
UNET Theta Warmup=0
UNET ZTol=0
UNET ZSATol=0
UNET MxIter=0
UNET MaxInSteps=0
UNET DtIC=0
UNET DtMin=0
UNET MaxCRTS=0
UNET WFStab=0
UNET SFStab=0
UNET WFX=0
UNET SFX=0
UNET DSS MLevel=0
UNET DZMax Abort=0
UNET Convert EG Bridges=0
UNET Use Existing IB Tables=0
UNET Froude Limit=0
UNET Froude Power=0
Write IC File=0
Echo Input=False
Echo Output=False
Write Detailed=0

--- Harmon Branch A.f01 (steady flow) ---

Flow Title=NFF Regression Equation
Program Version=4.00
Number of Profiles=1
Profile Names=P100yr
River Rch & RM=Harmon Branch A,Main      ,10485.4
440.1672
River Rch & RM=Harmon Branch A,Main      ,10351.4
660.0467
River Rch & RM=Harmon Branch A,Main      ,9708.2
672.9886
River Rch & RM=Harmon Branch A,Main      ,6593.4
741.9188
River Rch & RM=Harmon Branch A,Main      ,6593.4
830.8342
River Rch & RM=Harmon Branch A,Main      ,5305.8
922.4909
River Rch & RM=Harmon Branch A,Main      ,3284.4
1022.983
River Rch & RM=Harmon Branch A,Main      ,155.7
1113.675
Boundary for River Rch & Prof#=Harmon Branch A,Main      ,1
Up Type=0
Dn Type=3
Dn Slope=0.036729

--- Harmon Branch A.g01 (geometry) ---

Geom Title=Geometry
Program Version=4.00

River Reach=Harmon Branch A ,Main
Reach XY= 30
     1823691.688       142517.08     1823624.908      142501.319
     1823560.225      142367.454      1823277.11      142109.669
      1822994.91      141967.587     1822745.007      141430.616
     1822573.796      141227.889     1822387.297      140711.091
     1822048.134      140349.687     1822019.605      140248.739
     1821909.884      140187.164     1821879.586      139985.125
     1821772.969      139989.154     1821665.757      140116.594
     1821614.031      140047.189     1821615.995      139826.537
     1821536.849      139659.841     1821631.709      139208.448
     1821648.956      138561.016     1821519.947      138218.453
     1821495.863      137488.772     1821249.153      137026.318
     1821294.057      136733.654     1821260.463      136564.545
     1821048.977       135789.97     1820796.241      135117.536
     1820658.742      134500.756     1820529.725      134183.137
     1820398.805      134107.903     1820095.584      133760.815

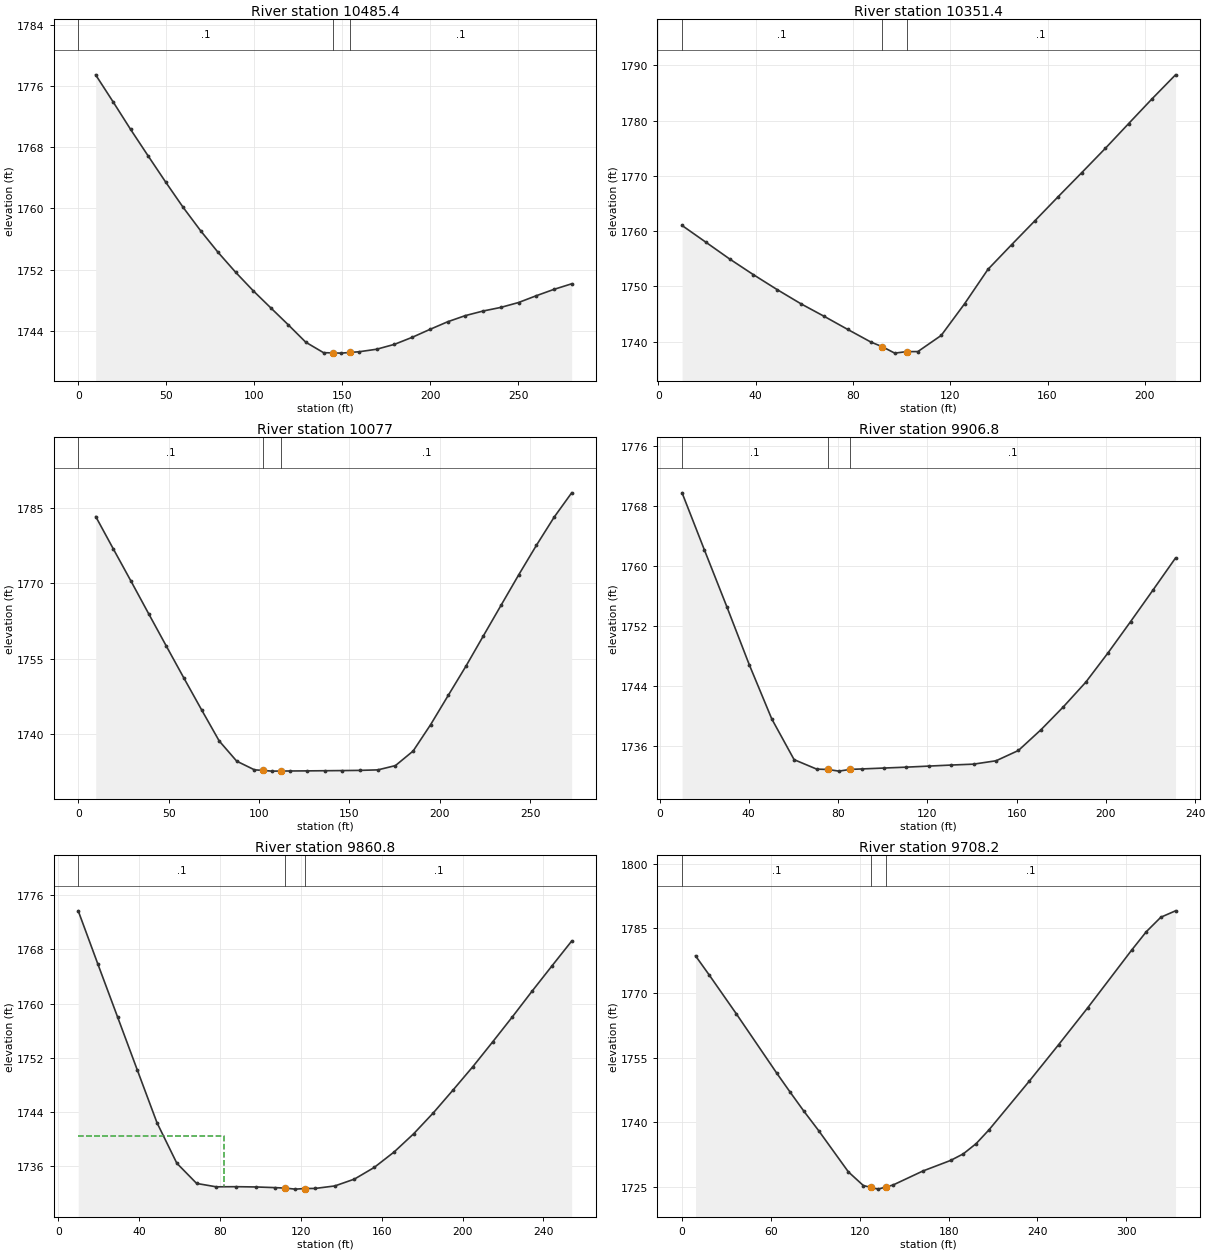
Type RM Length L Ch R = 1 ,10485.4 ,110.5,134,157.5
XS GIS Cut Line= 3
     1823737.976      142382.117     1823689.972      142491.303
     1823657.984      142649.241
#Sta/Elev= 30
     9.9 1777.48    19.9 1773.92    29.8 1770.33    39.8 1766.85    49.7 1763.45
    59.6 1760.15    69.6 1757.07    79.5 1754.25    89.5 1751.64    99.4 1749.24
   109.3 1747.02   119.3 1744.79   129.3  1742.5   139.4 1741.13   144.5  1741.1
   149.5 1741.07   154.5 1741.16   159.6 1741.25   169.6 1741.58   179.7 1742.22
   189.8 1743.14   199.8 1744.17   209.9 1745.17     220 1745.98   230.1 1746.58
   240.1 1747.05   250.2 1747.69   260.3 1748.58   270.3 1749.41   280.4 1750.14
#Mann= 3 , 0 , 0
       0      .1       0   144.5    .045       0   154.5      .1       0
Bank Sta=144.5,154.5
XS Rating Curve= 0 ,0
Exp/Cntr=0.3,0.1

Type RM Length L Ch R = 1 ,10351.4 ,286.6,274.4,262.2
XS GIS Cut Line= 4
     1823671.979      142387.344     1823630.995      142429.327
     1823556.024      142446.321     1823502.045      142501.299
#Sta/Elev= 24
     9.8 1761.02    19.6 1757.99    29.3 1754.98    39.1 1752.13    48.9 1749.42
    58.7 1746.85    68.3 1744.57    77.9 1742.22    87.5 1739.92    92.1  1739.1
   97.19 1737.94   102.1 1738.21   106.7 1738.22   116.3 1741.14   125.9 1746.86
   135.5 1753.08   145.2 1757.53   154.8 1761.87   164.4 1766.24   174.1 1770.59
   183.7 1774.94   193.3 1779.43     203 1783.94   212.6 1788.26
#Mann= 3 , 0 , 0
     9.8      .1       0    92.1    .045       0   102.1      .1       0
Bank Sta=92.1,102.1
XS Rating Curve= 0 ,0
Exp/Cntr=0.3,0.1

Type RM Length L Ch R = 1 ,10077   ,171.7,170.3,168.8
XS GIS Cut Line= 3
     1823499.004      142148.699     1823406.941      142249.478
     1823314.877      142350.258
#Sta/Elev= 30
     9.7 1783.27    19.5 1776.79    29.3 1770.37      39 1763.94    48.8 1757.49
    58.5 1751.15    68.3 1744.83      78 1738.67    87.7 1734.65    97.5 1732.93
   102.2 1732.81   107.2 1732.67   112.2 1732.69     117  1732.7   126.8 1732.72
   136.5 1732.75   146.2 1732.78     156 1732.82   165.8 1732.92   175.5 1733.77
   185.3 1736.67     195 1741.93   204.7 1747.72   214.5 1753.53   224.2 1759.59
     234 1765.68   243.7 1771.69   253.5 1777.56   263.3 1783.15     273 1787.99
#Mann= 3 , 0 , 0
       0      .1       0   102.2    .045       0   112.2      .1       0
Bank Sta=102.2,112.2
XS Rating Curve= 0 ,0
Exp/Cntr=0.3,0.1

Type RM Length L Ch R = 1 ,9906.8  ,47.8,45.9,44
XS GIS Cut Line= 2
     1823352.104      142048.477     1823208.161      142229.406
#Sta/Elev= 25
    10.1 1769.72    20.1 1762.12    30.2 1754.52    40.2 1746.83    50.3  1739.6
    60.3 1734.18    70.4 1732.92    75.4 1732.87    80.4 1732.65    85.4 1732.88
    90.5 1732.94   100.5 1733.06   110.6 1733.18   120.6 1733.32   130.7 1733.46
   140.7 1733.58   150.8 1734.03   160.8  1735.4   170.9 1738.16   180.9  1741.2
     191  1744.5     201 1748.42   211.1 1752.58   221.2 1756.81   231.2 1761.04
#Mann= 3 , 0 , 0
    10.1      .1       0    75.4    .045       0    85.4      .1       0
Bank Sta=75.4,85.4
XS Rating Curve= 0 ,0
Exp/Cntr=0.3,0.1

Type RM Length L Ch R = 1 ,9860.8  ,157.1,152.7,148.3
XS GIS Cut Line= 2
     1823310.359      142012.287     1823172.932      142225.863
#Sta/Elev= 28
     9.8 1773.67    19.5 1765.84    29.3    1758    39.1 1750.15    48.8 1742.41
    58.6 1736.45    68.4 1733.47    78.1 1732.97    87.9 1732.99    97.7 1732.95
   107.4 1732.85   112.2 1732.78   117.2 1732.63   122.2 1732.72     127 1732.73
   136.8  1733.1   146.5 1734.11   156.3 1735.83   166.1  1738.1   175.8 1740.79
   185.6  1743.9   195.4 1747.28   205.1 1750.69   214.9 1754.34   224.7 1758.05
   234.4 1761.82   244.2 1765.53     254 1769.21
#Mann= 3 , 0 , 0
     9.8      .1       0   112.2    .045       0   122.2      .1       0
#XS Ineff= 2 , 0
           82.05 1740.52
Permanent Ineff=
       F       F
Bank Sta=112.2,122.2
XS Rating Curve= 0 ,0
Exp/Cntr=0.3,0.1

Type RM Length L Ch R = 1 ,9708.2  ,220.9,242.7,264.5
XS GIS Cut Line= 5
     1823195.166      141916.529     1823141.187      141978.504
     1823110.199      142063.471     1823100.803      142114.561
     1823041.227      142205.415
#Sta/Elev= 25
     9.1 1778.64    18.3 1774.22    36.5 1765.27    63.9 1751.46    73.1 1746.98
    82.2 1742.65    92.2 1738.13   112.3 1728.55   122.4 1725.38   127.4 1724.96
   132.4 1724.55   137.4 1725.02   142.5 1725.51   162.6 1728.75   181.3  1731.2
   189.9 1732.73   198.6 1735.11   207.3 1738.32   234.5 1749.61   254.2 1758.02
     274 1766.64   303.6 1779.98   313.5 1784.25   323.3  1787.6   333.2 1789.08
#Mann= 3 , 0 , 0
       0      .1       0   127.4    .045       0   137.4      .1       0
Bank Sta=127.4,137.4
XS Rating Curve= 0 ,0
Exp/Cntr=0.3,0.1

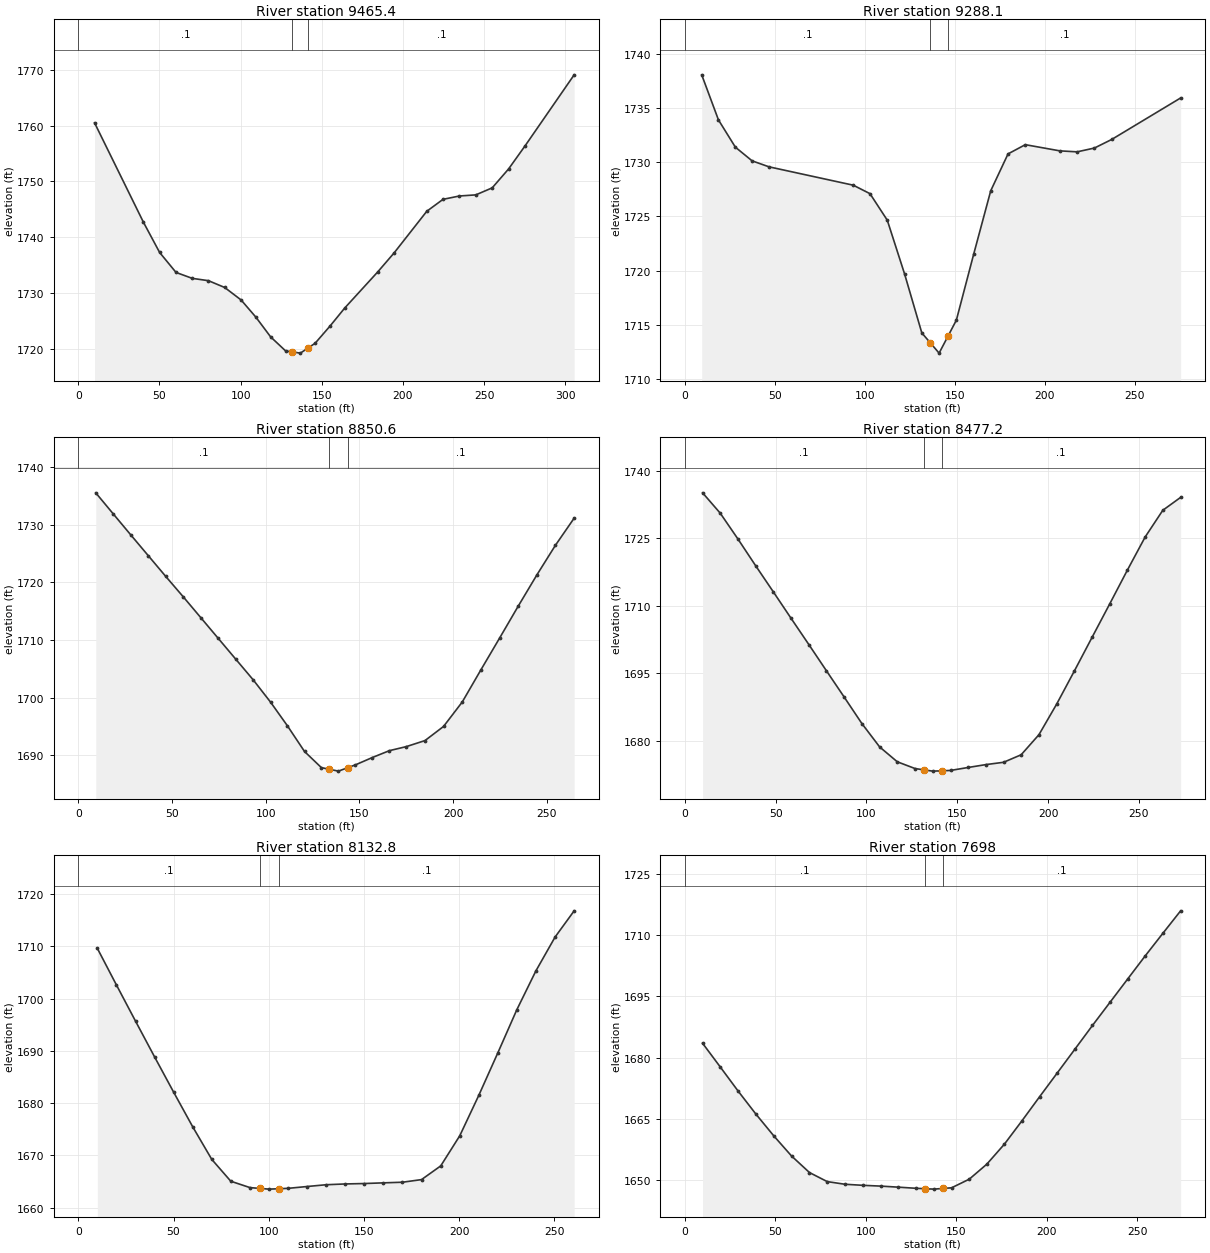
Type RM Length L Ch R = 1 ,9465.4  ,184,177.4,170.7
XS GIS Cut Line= 4
     1823096.205       141837.56     1823002.242      141872.546
     1822939.267      141883.542     1822830.309      141973.506
#Sta/Elev= 27
      10 1760.49    40.1 1742.67    50.1 1737.24    60.2 1733.66    70.2  1732.6
    80.2 1732.18    90.2 1730.96   100.3 1728.72   109.4 1725.64   118.5  1722.1
   127.7 1719.59   131.8 1719.41   136.8 1719.19   141.8 1720.16   145.9 1720.96
   155.1 1724.05   164.2  1727.3   184.4 1733.73   194.5 1737.14   214.7 1744.63
   224.7 1746.77   234.8 1747.37   244.9 1747.57     255 1748.83   265.1 1752.22
   275.2 1756.34   305.5  1769.1
#Mann= 3 , 0 , 0
       0      .1       0   131.8    .045       0   141.8      .1       0
Bank Sta=131.8,141.8
XS Rating Curve= 0 ,0
Exp/Cntr=0.3,0.1

Type RM Length L Ch R = 1 ,9288.1  ,445.4,437.5,429.5
XS GIS Cut Line= 3
     1822975.323       141663.67     1822896.283      141729.602
       1822744.1      141811.003
#Sta/Elev= 23
     9.4 1738.04    18.7 1733.89    28.1 1731.38    37.4 1730.12    46.8 1729.57
    93.6 1727.88   102.9  1727.1   112.5 1724.66   122.1 1719.72   131.7 1714.28
   136.3 1713.39   141.3 1712.42   146.3    1714   150.9 1715.46   160.5 1721.52
     170 1727.37   179.6 1730.76   189.2 1731.61   208.4 1731.04     218 1730.95
   227.6  1731.3   237.2 1732.09   275.5 1735.91
#Mann= 3 , 0 , 0
       0      .1       0   136.3    .045       0   146.3      .1       0
Bank Sta=136.3,146.3
XS Rating Curve= 0 ,0
Exp/Cntr=0.3,0.1

Type RM Length L Ch R = 1 ,8850.6  ,364.5,373.4,382.3
XS GIS Cut Line= 4
     1822807.318       141301.77     1822708.357       141328.76
     1822662.375      141384.738     1822613.395      141459.708
#Sta/Elev= 30
     9.3 1735.54    18.7 1731.86      28 1728.24    37.3 1724.65    46.6 1721.06
      56  1717.5    65.3 1713.91    74.6 1710.32    83.9 1706.73    93.3 1703.11
   102.6 1699.23   111.6 1695.12   120.7 1690.68   129.7 1687.88   133.8  1687.6
   138.8 1687.27   143.8 1687.87   147.9 1688.36   156.9 1689.63     166 1690.82
     175 1691.52     185 1692.57   194.9 1695.02   204.9 1699.27   214.8 1704.82
   224.8 1710.34   234.7 1715.86   244.7  1721.3   254.6 1726.44   264.6 1731.15
#Mann= 3 , 0 , 0
       0      .1       0   133.8    .045       0   143.8      .1       0
Bank Sta=133.8,143.8
XS Rating Curve= 0 ,0
Exp/Cntr=0.3,0.1

Type RM Length L Ch R = 1 ,8477.2  ,345.4,344.4,343.5
XS GIS Cut Line= 3
     1822636.342       140981.56     1822512.994      141040.019
     1822389.646      141098.479
#Sta/Elev= 30
     9.8 1735.09    19.5 1730.58    29.3 1724.82      39 1718.92    48.8 1713.08
    58.5 1707.25    68.3 1701.42      78 1695.59    87.8 1689.74    97.5 1683.89
   107.3 1678.69     117  1675.4   126.8  1673.9   131.5 1673.62   136.5 1673.33
   141.5  1673.4   146.3 1673.48     156 1674.14   165.8 1674.78   175.5 1675.29
   185.2 1676.96     195 1681.42   204.7 1688.17   214.5 1695.56   224.2 1702.99
     234 1710.47   243.7 1717.95   253.5 1725.31   263.2 1731.22     273 1734.08
#Mann= 3 , 0 , 0
       0      .1       0   131.5    .045       0   141.5      .1       0
Bank Sta=131.5,141.5
XS Rating Curve= 0 ,0
Exp/Cntr=0.3,0.1

Type RM Length L Ch R = 1 ,8132.8  ,442.3,434.8,427.4
XS GIS Cut Line= 2
     1822476.074      140672.643     1822246.164      140795.094
#Sta/Elev= 28
      10 1709.58      20  1702.6    30.1 1695.64    40.1 1688.81    50.1 1682.08
    60.1 1675.47    70.1 1669.25    80.1 1665.07    90.2 1663.85    95.2  1663.7
   100.2 1663.56   105.2 1663.63   110.2 1663.71   120.2 1664.06   130.2  1664.4
   140.3 1664.55   150.3 1664.63   160.3 1664.76   170.3 1664.88   180.3 1665.38
   190.4    1668   200.4 1673.76   210.4 1681.49   220.4 1689.61   230.4 1697.87
   240.4 1705.28   250.5 1711.76   260.5 1716.76
#Mann= 3 , 0 , 0
       0      .1       0    95.2    .045       0   105.2      .1       0
Bank Sta=95.2,105.2
XS Rating Curve= 0 ,0
Exp/Cntr=0.3,0.1

Type RM Length L Ch R = 1 ,7698    ,300.4,303.9,307.1
XS GIS Cut Line= 3
     1822193.148      140293.597     1822103.155       140397.83
      1822013.41      140500.397
#Sta/Elev= 30
     9.8 1683.54    19.7 1677.67    29.5 1671.82    39.3 1666.21    49.2 1660.88
      59 1655.97    68.9 1651.93    78.7 1649.72    88.5 1649.07    98.4 1648.81
   108.2 1648.62     118 1648.36   127.9 1648.08   132.7 1647.98   137.7 1647.88
   142.7 1648.05   147.4  1648.2   157.2 1650.31   166.9 1653.98   176.6 1658.86
   186.4 1664.62   196.1 1670.47   205.9 1676.31   215.6 1682.09   225.3 1687.88
   235.1  1693.6   244.8 1699.26   254.5 1704.91   264.3 1710.45     274 1715.88
#Mann= 3 , 0 , 0
       0      .1       0   132.7    .045       0   142.7      .1       0
Bank Sta=132.7,142.7
XS Rating Curve= 0 ,0
Exp/Cntr=0.3,0.1

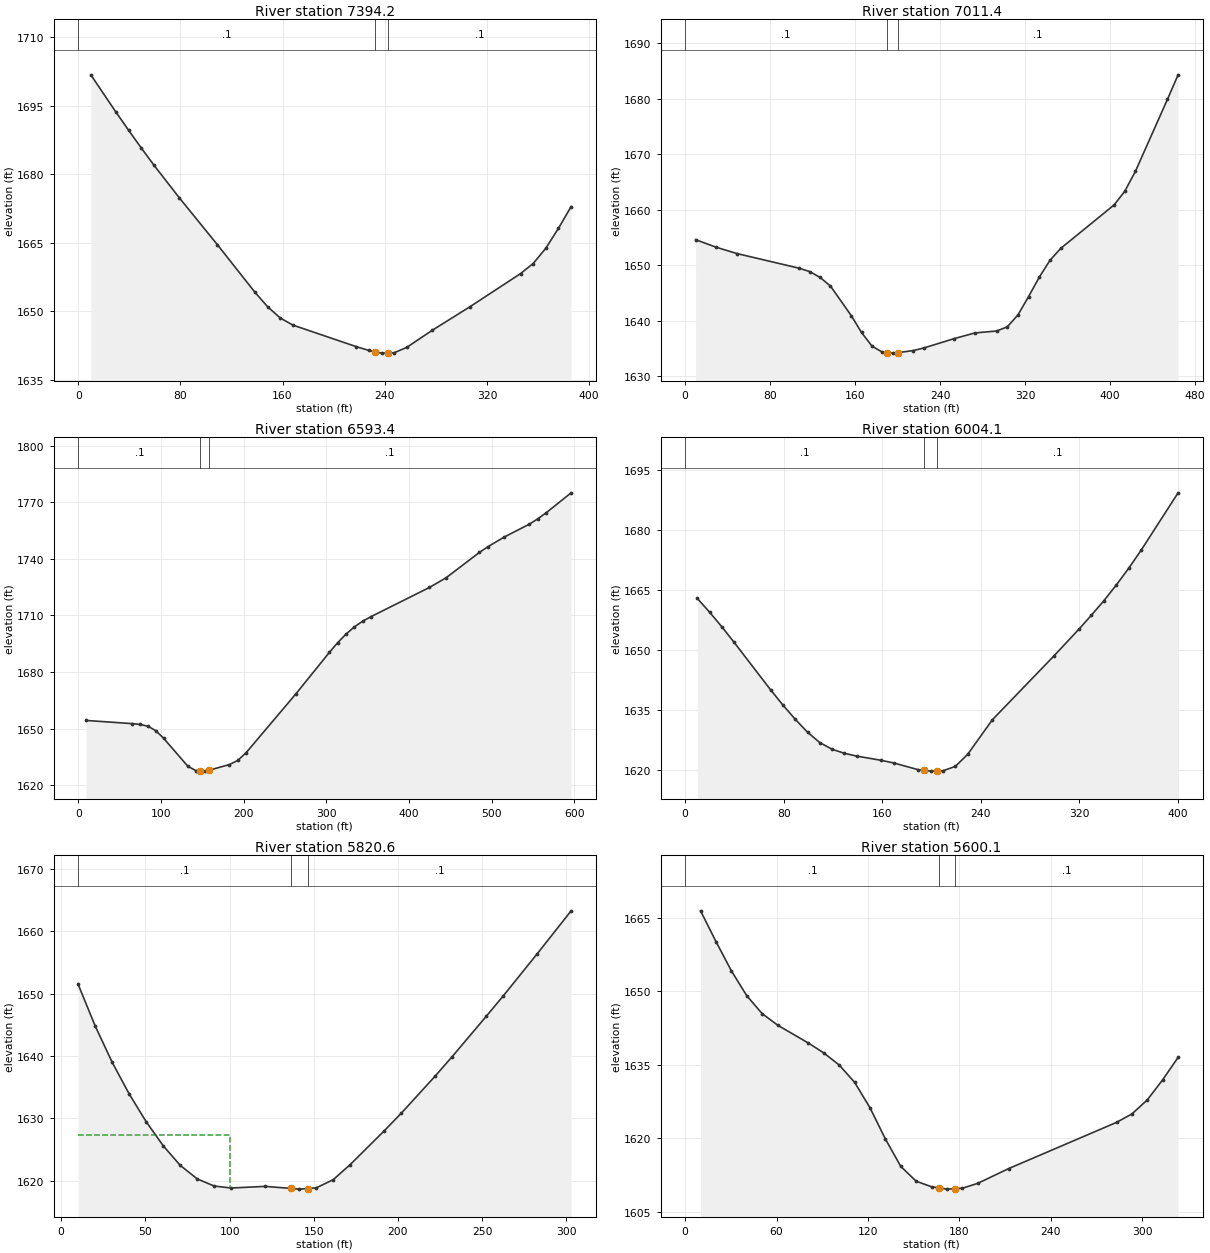
Type RM Length L Ch R = 1 ,7394.2  ,401.8,382.8,366.9
XS GIS Cut Line= 2
     1822091.225      140020.399      1821810.79      140285.529
#Sta/Elev= 25
     9.9 1701.72    29.7 1693.51    39.6 1689.55    49.5 1685.68    59.4 1681.93
    79.2 1674.82   108.9  1664.6   138.5 1654.13   148.4 1650.97   158.3 1648.52
   168.2 1646.98   217.7 1642.28   227.6 1641.44   232.5 1641.16   237.5 1640.86
   242.5  1640.9   247.4 1640.94   257.3 1642.13   277.1 1645.84   306.8 1651.02
   346.3 1658.25   356.2 1660.46   366.1  1663.8     376 1668.16   385.9 1672.91
#Mann= 3 , 0 , 0
       0      .1       0   232.5    .045       0   242.5      .1       0
Bank Sta=232.5,242.5
XS Rating Curve= 0 ,0
Exp/Cntr=0.3,0.1

Type RM Length L Ch R = 1 ,7011.4  ,381.9,418,448
XS GIS Cut Line= 4
     1821833.357      139874.987      1821719.34      139967.139
     1821738.082      140092.089     1821709.968      140281.078
#Sta/Elev= 30
     9.8 1654.59    29.3 1653.22    48.9 1652.08   107.5 1649.44   117.3 1648.84
   127.1 1647.78   136.8 1646.23   156.3 1640.93     166 1637.88   175.8 1635.44
   185.5 1634.34   190.2 1634.25   195.2 1634.16   200.2 1634.24   214.6 1634.62
   224.4 1635.07   253.5 1636.79   272.9  1637.8   293.1 1638.14   303.1 1638.88
   313.2 1641.02   323.2 1644.32   333.3 1647.83   343.3 1650.84   353.4    1653
   403.7 1660.83   413.7 1663.27   423.8 1666.88     454 1679.86     464 1684.27
#Mann= 3 , 0 , 0
       0      .1       0   190.2    .045       0   200.2      .1       0
Bank Sta=190.2,200.2
XS Rating Curve= 0 ,0
Exp/Cntr=0.3,0.1

Type RM Length L Ch R = 1 ,6593.4  ,584.1,589.3,595
XS GIS Cut Line= 4
     1821755.263      139806.264     1821647.493      139839.064
     1821567.837      139849.997     1821253.898      140103.023
#Sta/Elev= 30
     9.4 1654.31    65.7  1652.6    75.1 1652.17    84.5 1651.21    93.9 1648.85
   103.3 1644.88   132.8 1629.92   142.8 1627.61   147.9 1627.51   152.9 1627.41
   157.9 1627.83     183  1630.9   193.1  1633.1   203.1 1637.16   263.6 1668.54
   303.9 1690.44     314 1695.61   324.1 1700.15   334.2 1703.98   344.3    1707
   354.3 1709.41   424.9 1724.87   445.1 1730.01   485.4 1743.48   495.5 1746.45
   515.6 1751.67   545.9 1758.48   555.9 1761.26     566 1764.45   596.3 1775.08
#Mann= 3 , 0 , 0
       0      .1       0   147.9    .045       0   157.9      .1       0
Bank Sta=147.9,157.9
XS Rating Curve= 0 ,0
Exp/Cntr=0.3,0.1

Type RM Length L Ch R = 1 ,6004.1  ,184.7,183.5,181.6
XS GIS Cut Line= 4
     1821772.444      139348.632     1821656.864      139290.842
     1821538.161      139272.099     1821397.591      139326.765
#Sta/Elev= 30
     9.9 1662.91    19.9 1659.47    29.8 1655.83    39.8 1651.94    69.6 1640.01
    79.5 1636.25    89.5 1632.71    99.4  1629.5   109.3 1626.93   119.3 1625.26
   129.2 1624.26   139.2 1623.56   159.3 1622.49   169.3 1621.84   189.3 1620.15
   194.3 1619.98   199.3  1619.8   204.3 1619.85   209.3 1619.89   219.4 1620.99
   229.4 1624.01   249.4 1632.62   299.7 1648.66   319.8 1655.28   329.8 1658.73
   339.9 1662.33   349.9 1666.21     360 1670.41   370.1 1674.91   400.2 1689.29
#Mann= 3 , 0 , 0
       0      .1       0   194.3    .045       0   204.3      .1       0
Bank Sta=194.3,204.3
XS Rating Curve= 0 ,0
Exp/Cntr=0.3,0.1

Type RM Length L Ch R = 1 ,5820.6  ,222.6,220.5,218.4
XS GIS Cut Line= 2
     1821760.932      139120.767     1821458.824      139099.852
#Sta/Elev= 25
    10.1 1651.45    20.2 1644.79    30.3 1638.96    40.4 1633.88    50.5 1629.43
    60.6 1625.58    70.7 1622.44    80.8 1620.27    90.8 1619.13   100.9 1618.81
   121.1 1619.07   136.3 1618.75   141.3 1618.63   146.3 1618.73   151.4 1618.83
   161.5 1620.14   171.6 1622.56   191.8 1627.97   201.9 1630.79   222.1 1636.76
   232.2 1639.89   252.4 1646.34   262.5 1649.62   282.6 1656.35   302.8 1663.26
#Mann= 3 , 0 , 0
    10.1      .1       0   136.3    .045       0   146.3      .1       0
#XS Ineff= 2 , 0
          100.42 1627.27
Permanent Ineff=
       F       F
Bank Sta=136.3,146.3
XS Rating Curve= 0 ,0
Exp/Cntr=0.3,0.1

Type RM Length L Ch R = 1 ,5600.1  ,294.6,294.3,294.1
XS GIS Cut Line= 2
     1821800.558      138890.999     1821477.247      138901.932
#Sta/Elev= 26
    10.1 1666.42    20.2 1660.16    30.3  1654.2    40.4 1649.11    50.5 1645.45
    60.7 1643.09    80.9 1639.43      91 1637.42   101.1 1634.96   111.2 1631.43
   121.3 1626.23   131.4 1619.87   141.5 1614.27   151.6 1611.25   161.7 1610.11
   166.9 1609.87   171.9 1609.63   176.9 1609.73     182 1609.82   192.1 1610.82
   212.3 1613.82   283.1 1623.25   293.2 1624.97   303.3 1627.84   313.4 1631.95
   323.5 1636.51
#Mann= 3 , 0 , 0
       0      .1       0   166.9    .045       0   176.9      .1       0
Bank Sta=166.9,176.9
XS Rating Curve= 0 ,0
Exp/Cntr=0.3,0.1

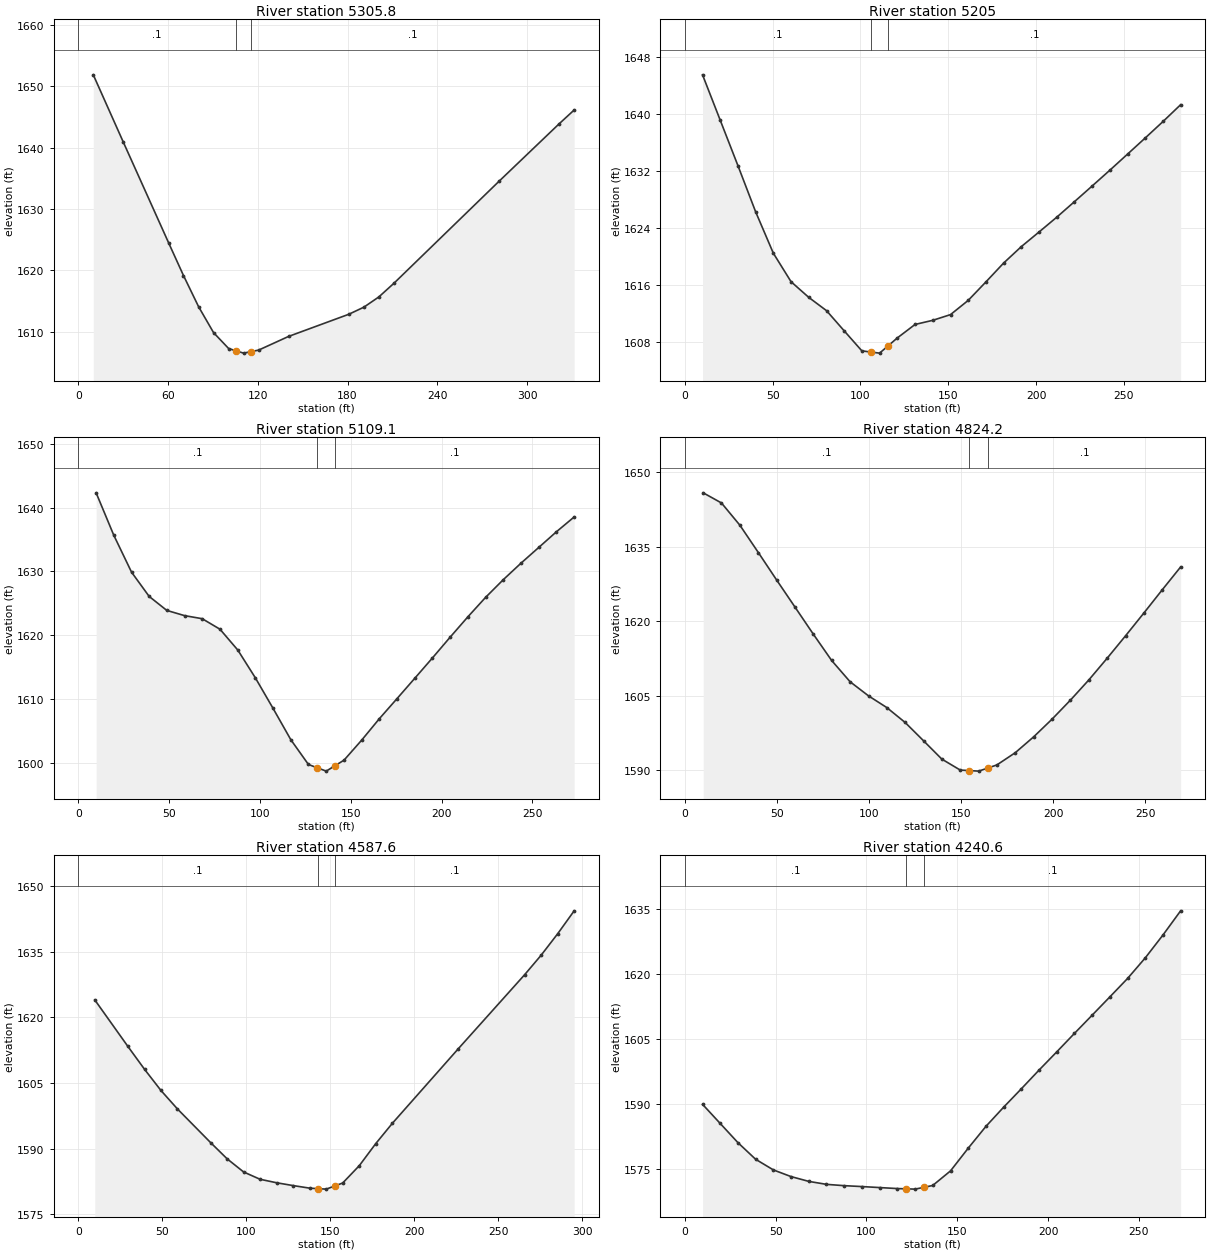
Type RM Length L Ch R = 1 ,5305.8  ,103.9,100.8,97.6
XS GIS Cut Line= 2
     1821764.634      138600.488     1821433.515      138616.107
#Sta/Elev= 19
      10  1651.9    30.1  1640.9    60.3 1624.51    70.3 1619.14    80.4 1614.05
    90.4 1609.82   100.5 1607.22   105.5 1606.84   110.5 1606.47   115.5 1606.72
   120.5 1606.96   140.6  1609.2   180.8 1612.81   190.9 1613.97   200.9 1615.64
   210.9 1617.85   281.3 1634.53   321.4 1643.89   331.5 1646.16
#Mann= 3 , 0 , 0
       0      .1       0   105.5    .045       0   115.5      .1       0
Bank Sta=105.5,115.5
XS Rating Curve= 0 ,0
Exp/Cntr=0.3,0.1

Type RM Length L Ch R = 1 ,5205    ,98.8,95.9,93
XS GIS Cut Line= 2
     1821738.855      138486.341      1821462.31      138543.277
#Sta/Elev= 30
    10.1 1645.46    20.2 1639.08    30.3  1632.7    40.3 1626.28    50.4 1620.46
    60.5 1616.46    70.6 1614.26    80.7  1612.4    90.8 1609.56   100.8 1606.77
   105.9  1606.6   110.9 1606.45   115.9  1607.5     121 1608.58   131.1 1610.47
   141.2 1611.05   151.3 1611.85   161.3 1613.83   171.4 1616.42   181.5 1619.07
   191.6 1621.38   201.7 1623.43   211.8 1625.51   221.8 1627.67   231.9 1629.87
     242 1632.09   252.1 1634.35   262.2 1636.62   272.3 1638.92   282.3 1641.27
#Mann= 3 , 0 , 0
       0      .1       0   105.9    .045       0   115.9      .1       0
Bank Sta=105.9,115.9
XS Rating Curve= 0 ,0
Exp/Cntr=0.3,0.1

Type RM Length L Ch R = 1 ,5109.1  ,279.1,285,290.9
XS GIS Cut Line= 3
     1821723.637      138372.821     1821595.251      138419.183
     1821466.865      138465.544
#Sta/Elev= 30
     9.8 1642.32    19.5 1635.69    29.3 1629.89      39 1626.09    48.7  1623.9
    58.5 1623.08    68.2  1622.6      78 1620.95    87.8 1617.69    97.5 1613.32
   107.2 1608.56     117 1603.64   126.7 1599.76   131.5 1599.25   136.5 1598.72
   141.5  1599.6   146.3 1600.44     156 1603.57   165.7 1606.92   175.5 1610.09
   185.2 1613.25     195 1616.46   204.7  1619.7   214.5  1622.9   224.2 1625.93
     234 1628.72   243.7 1631.29   253.5 1633.76   263.2 1636.21     273 1638.54
#Mann= 3 , 0 , 0
       0      .1       0   131.5    .045       0   141.5      .1       0
Bank Sta=131.5,141.5
XS Rating Curve= 0 ,0
Exp/Cntr=0.3,0.1

Type RM Length L Ch R = 1 ,4824.2  ,235.6,236.5,237.5
XS GIS Cut Line= 2
     1821681.854      138141.294      1821413.21      138156.912
#Sta/Elev= 29
      10 1645.83    19.9 1643.79    29.9 1639.31    39.9 1633.82    49.8 1628.31
    59.8 1622.84    69.8 1617.36    79.7 1612.09    89.7 1607.81    99.7 1604.97
   109.6 1602.62   119.6 1599.61   129.6 1595.92   139.5 1592.24   149.5 1590.03
   154.5 1589.93   159.5 1589.82   164.5 1590.45   169.4 1591.07   179.4 1593.54
   189.4 1596.74   199.3 1600.27   209.3 1604.11   219.3 1608.18   229.2 1612.53
   239.2 1617.05   249.2 1621.66   259.1  1626.3   269.1 1630.91
#Mann= 3 , 0 , 0
       0      .1       0   154.5    .045       0   164.5      .1       0
Bank Sta=154.5,164.5
XS Rating Curve= 0 ,0
Exp/Cntr=0.3,0.1

Type RM Length L Ch R = 1 ,4587.6  ,348.9,347,345.2
XS GIS Cut Line= 2
     1821667.797      137916.382     1821372.601      137919.506
#Sta/Elev= 24
     9.8 1623.98    29.5 1613.36    39.4 1608.14    49.2 1603.29      59 1599.08
    78.7 1591.41    88.6 1587.68    98.4 1584.68   108.2 1583.01   118.1 1582.21
   127.9 1581.57   137.8 1580.98   142.6 1580.87   147.6 1580.76   152.6 1581.47
   157.4 1582.16   167.3 1586.13   177.1 1591.17     187 1595.81   226.3 1612.86
   265.7 1629.73   275.5 1634.17   285.4  1639.1   295.2 1644.33
#Mann= 3 , 0 , 0
       0      .1       0   142.6    .045       0   152.6      .1       0
Bank Sta=142.6,152.6
XS Rating Curve= 0 ,0
Exp/Cntr=0.3,0.1

Type RM Length L Ch R = 1 ,4240.6  ,409.4,405.3,401.1
XS GIS Cut Line= 3
     1821627.412      137563.257     1821491.648       137577.41
     1821355.884      137591.563
#Sta/Elev= 30
     9.8 1589.95    19.5 1585.55    29.3 1581.11      39  1577.3    48.8 1574.84
    58.5 1573.31    68.3  1572.2      78 1571.52    87.7 1571.22    97.5 1571.01
   107.3 1570.78     117 1570.55   121.8 1570.49   126.8 1570.42   131.8 1570.85
   136.5 1571.26   146.3 1574.62     156 1579.83   165.8 1584.88   175.5 1589.28
   185.3 1593.54     195 1597.83   204.8 1602.05   214.5 1606.29   224.3 1610.51
     234  1614.7   243.8 1618.97   253.5 1623.69   263.3 1628.99     273 1634.55
#Mann= 3 , 0 , 0
       0      .1       0   121.8    .045       0   131.8      .1       0
Bank Sta=121.8,131.8
XS Rating Curve= 0 ,0
Exp/Cntr=0.3,0.1

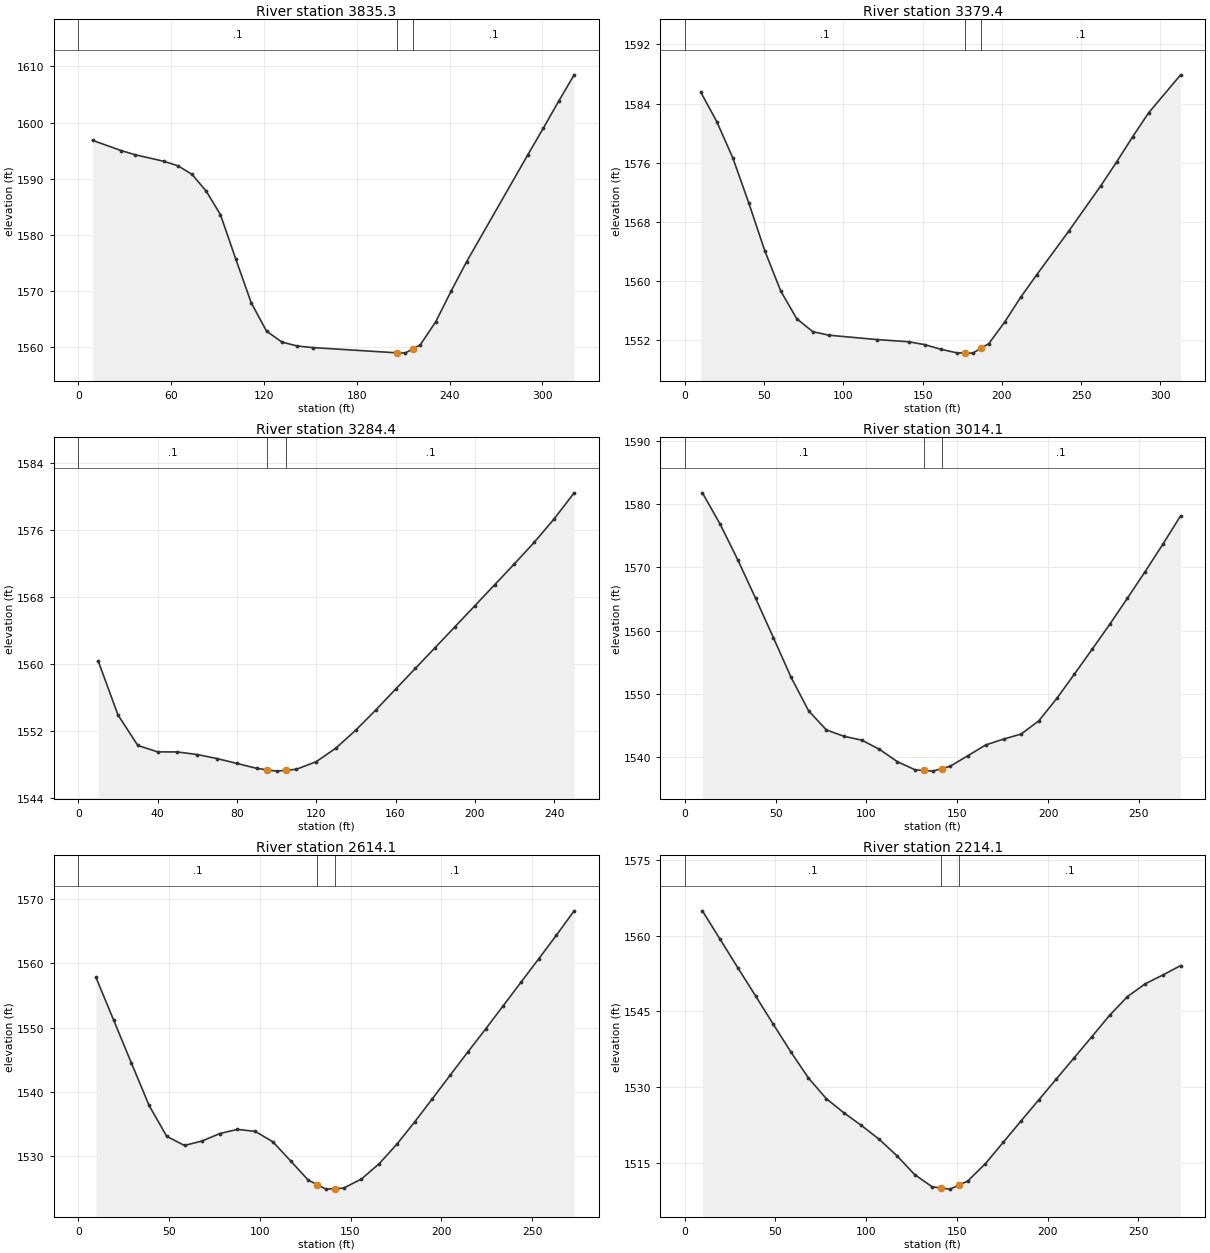
Type RM Length L Ch R = 1 ,3835.3  ,446.9,455.9,464.9
XS GIS Cut Line= 3
     1821525.666      137211.971       1821438.2      137183.857
     1821221.098      137255.704
#Sta/Elev= 25
     9.2 1596.82    27.6    1595    36.7 1594.25    55.1 1593.09    64.3 1592.29
    73.5 1590.75    82.7 1587.75    91.9 1583.55   101.8 1575.64   111.8 1567.82
   121.7 1562.77   131.6 1560.82   141.6 1560.11   151.5 1559.83   206.2 1558.89
   211.2 1558.84   216.2 1559.59   221.1 1560.32   231.1 1564.45     241 1569.89
     251 1575.13   290.7 1594.27   300.7 1599.01   310.6 1603.81   320.6 1608.51
#Mann= 3 , 0 , 0
       0      .1       0   206.2    .045       0   216.2      .1       0
Bank Sta=206.2,216.2
XS Rating Curve= 0 ,0
Exp/Cntr=0.3,0.1

Type RM Length L Ch R = 1 ,3379.4  ,101,95,89.1
XS GIS Cut Line= 2
     1821442.886      136812.128      1821132.07      136777.767
#Sta/Elev= 27
    10.1 1585.53    20.2 1581.54    30.3 1576.63    40.3 1570.57    50.4 1564.09
    60.5 1558.62    70.6 1554.86    80.7 1553.11    90.8 1552.63     121 1552.04
   141.2 1551.74   151.3 1551.35   161.4 1550.73   171.5 1550.24   176.6 1550.22
   181.6  1550.2   186.6 1550.84   191.7 1551.48   201.7  1554.4   211.8 1557.76
   221.9  1560.8   242.1 1566.71   262.3 1572.85   272.4 1576.11   282.4 1579.49
   292.5 1582.74   312.7 1587.89
#Mann= 3 , 0 , 0
       0      .1       0   176.6    .045       0   186.6      .1       0
Bank Sta=176.6,186.6
XS Rating Curve= 0 ,0
Exp/Cntr=0.3,0.1

Type RM Length L Ch R = 1 ,3284.4  ,270,270.2,270.5
XS GIS Cut Line= 3
     1821396.029      136684.054     1821228.907      136715.291
     1821149.251      136723.101
#Sta/Elev= 27
      10 1560.32      20 1553.86      30 1550.22      40 1549.45      50 1549.44
      60 1549.13      70 1548.65      80 1548.07      90 1547.48      95 1547.31
     100 1547.15     105 1547.26     110 1547.37     120 1548.28     130 1549.91
     140 1552.06     150 1554.44     160 1556.94     170 1559.42     180 1561.91
     190  1564.4     200  1566.9     210 1569.41     220 1571.92     230 1574.49
     240 1577.28   250.1 1580.39
#Mann= 3 , 0 , 0
       0      .1       0      95    .045       0     105      .1       0
Bank Sta=95,105
XS Rating Curve= 0 ,0
Exp/Cntr=0.3,0.1

Type RM Length L Ch R = 1 ,3014.1  ,403.7,400,396.5
XS GIS Cut Line= 3
     1821352.061      136421.353     1821217.604      136444.883
     1821083.147      136468.413
#Sta/Elev= 30
     9.7 1581.75    19.5 1576.78    29.2 1571.15      39 1565.08    48.8 1558.87
    58.5 1552.62    68.2 1547.31      78 1544.29    87.7 1543.29    97.5 1542.68
   107.2 1541.23     117 1539.29   126.8    1538   131.5  1537.9   136.5 1537.79
   141.5 1538.19   146.2 1538.57     156 1540.25   165.7 1541.93   175.5 1542.85
   185.2 1543.65     195 1545.76   204.8 1549.27   214.5 1553.11   224.2 1557.01
     234    1561   243.7 1565.11   253.5 1569.32   263.3 1573.67     273 1578.12
#Mann= 3 , 0 , 0
       0      .1       0   131.5    .045       0   141.5      .1       0
Bank Sta=131.5,141.5
XS Rating Curve= 0 ,0
Exp/Cntr=0.3,0.1

Type RM Length L Ch R = 1 ,2614.1  ,398.2,400,400.3
XS GIS Cut Line= 3
     1821249.695      136009.347     1821121.983      136057.415
     1820993.473      136104.111
#Sta/Elev= 30
     9.7 1557.83    19.5 1551.14    29.2 1544.51      39 1537.87    48.7 1533.07
    58.5 1531.64    68.2 1532.34      78  1533.5    87.7 1534.15    97.5 1533.83
   107.2 1532.21     117 1529.23   126.7 1526.24   131.5 1525.55   136.5 1524.84
   141.5 1524.92   146.2    1525     156 1526.42   165.8 1528.81   175.5 1531.84
   185.3  1535.3   195.1 1538.93   204.8 1542.56   214.6  1546.2   224.4 1549.78
   234.1  1553.4   243.9 1557.07   253.7 1560.73   263.4 1564.39   273.2 1568.19
#Mann= 3 , 0 , 0
       0      .1       0   131.5    .045       0   141.5      .1       0
Bank Sta=131.5,141.5
XS Rating Curve= 0 ,0
Exp/Cntr=0.3,0.1

Type RM Length L Ch R = 1 ,2214.1  ,402.4,400,398.9
XS GIS Cut Line= 3
     1821132.181      135645.256     1821000.507      135680.949
     1820870.977      135725.401
#Sta/Elev= 30
     9.7 1564.94    19.5 1559.28    29.2 1553.68      39 1548.09    48.7  1542.5
    58.5 1536.96    68.2 1531.79      78 1527.71    87.7  1524.9    97.4 1522.38
   107.2 1519.64   116.9 1516.41   126.7 1512.66   136.4 1510.22   141.2 1509.99
   146.2 1509.76   151.2 1510.57     156 1511.36   165.8 1514.83   175.6 1519.05
   185.3 1523.24   195.1 1527.42   204.9 1531.62   214.7  1535.8   224.5 1540.01
   234.2  1544.2     244 1547.91   253.8 1550.45   263.6 1552.22   273.4 1554.08
#Mann= 3 , 0 , 0
       0      .1       0   141.2    .045       0   151.2      .1       0
Bank Sta=141.2,151.2
XS Rating Curve= 0 ,0
Exp/Cntr=0.3,0.1

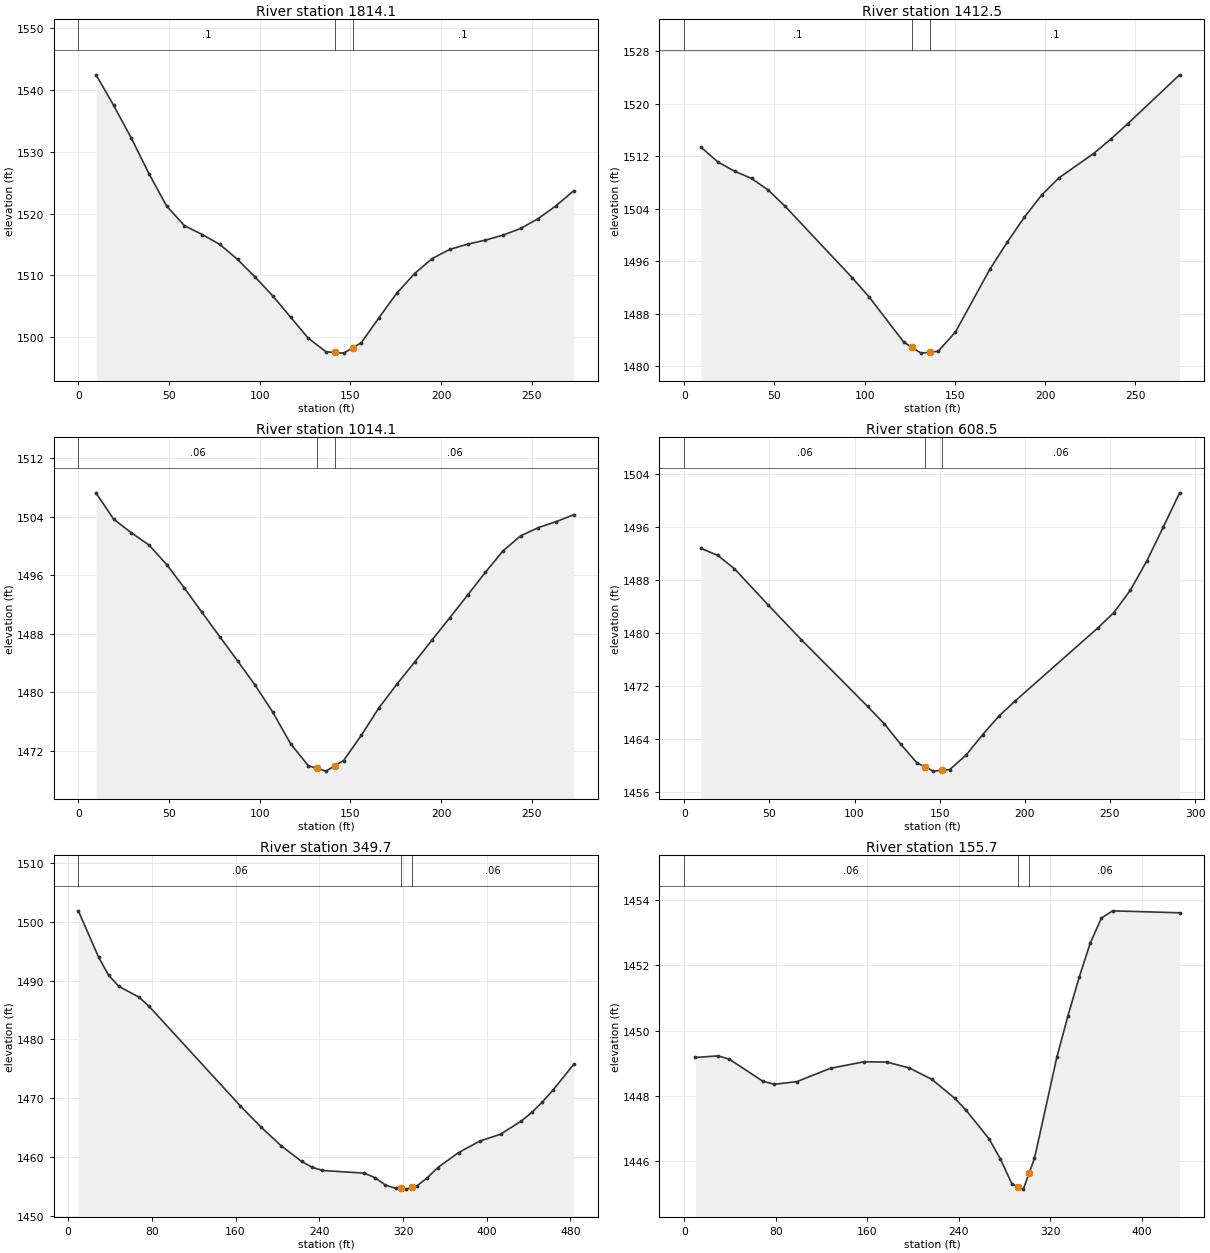
Type RM Length L Ch R = 1 ,1814.1  ,399.3,401.7,404.1
XS GIS Cut Line= 3
     1820990.261       135257.65      1820863.66      135308.683
     1820737.058      135359.716
#Sta/Elev= 30
     9.8 1542.44    19.5 1537.48    29.2 1532.21      39 1526.41    48.7 1521.21
    58.5 1518.04    68.3 1516.61      78 1515.01    87.8 1512.57    97.5 1509.71
   107.2 1506.67     117 1503.25   126.7 1499.85   136.5 1497.64   141.2 1497.53
   146.3 1497.42   151.2 1498.28     156 1499.12   165.7 1503.15   175.5 1507.11
   185.3 1510.28     195 1512.72   204.8 1514.21   214.5 1515.04   224.3  1515.7
     234  1516.5   243.8 1517.59   253.5 1519.19   263.3 1521.26     273 1523.68
#Mann= 3 , 0 , 0
       0      .1       0   141.2    .045       0   151.2      .1       0
Bank Sta=141.2,151.2
XS Rating Curve= 0 ,0
Exp/Cntr=0.3,0.1

Type RM Length L Ch R = 1 ,1412.5  ,400.1,398.3,396.5
XS GIS Cut Line= 3
     1820885.678      134904.778      1820783.77      134915.998
     1820617.819      134961.233
#Sta/Elev= 23
     9.3 1513.38    18.6 1511.14      28  1509.7    37.3 1508.62    46.6 1506.83
    55.9 1504.37    93.2 1493.45   102.5 1490.54   121.6 1483.69   126.2 1482.87
   131.2 1481.99   136.2 1482.13   140.7 1482.26   150.3 1485.22   169.4 1494.79
     179 1498.91   188.5 1502.72   198.1  1506.1   207.6 1508.69   226.8 1512.41
   236.3  1514.6   245.9 1516.99   274.5 1524.41
#Mann= 3 , 0 , 0
       0      .1       0   126.2    .045       0   136.2      .1       0
Bank Sta=126.2,136.2
XS Rating Curve= 0 ,0
Exp/Cntr=0.3,0.1

Type RM Length L Ch R = 1 ,1014.1  ,413.7,405.6,397.6
XS GIS Cut Line= 3
     1820804.348      134500.954     1820676.319      134548.292
      1820548.29      134595.631
#Sta/Elev= 30
     9.7 1507.28    19.5 1503.67    29.2 1501.82      39 1500.13    48.7 1497.47
    58.5 1494.24    68.2 1490.91      78 1487.59    87.8 1484.28    97.5 1480.94
   107.2 1477.26     117 1472.95   126.8 1469.93   131.5 1469.58   136.5  1469.2
   141.5 1469.95   146.2 1470.65     156 1474.11   165.7 1477.87   175.5 1481.07
   185.3  1484.1     195 1487.16   204.8 1490.21   214.5 1493.27   224.3 1496.39
     234 1499.32   243.8  1501.4   253.5 1502.52   263.3 1503.33     273 1504.28
#Mann= 3 , 0 , 0
       0     .06       0   131.5    .045       0   141.5     .06       0
Bank Sta=131.5,141.5
XS Rating Curve= 0 ,0
Exp/Cntr=0.3,0.1

Type RM Length L Ch R = 1 ,608.5   ,258.8,258.8,258.8
XS GIS Cut Line= 3
     1820647.869      134120.086     1820561.982      134141.303
     1820413.662      134279.052
#Sta/Elev= 23
     9.8 1492.77    19.7  1491.7    29.5 1489.69    49.1 1484.29    68.8 1478.99
   107.7 1468.95   117.4 1466.36     127 1463.29   136.7 1460.44   141.3 1459.85
   146.3  1459.2   151.3 1459.32   155.9 1459.43   165.6 1461.64   175.2 1464.69
   184.9 1467.52   194.5 1469.81   242.7 1480.73   252.3 1483.09     262 1486.47
   271.6 1490.85   281.2 1495.91   290.9 1501.13
#Mann= 3 , 0 , 0
       0     .06       0   141.3    .045       0   151.3     .06       0
Bank Sta=141.3,151.3
XS Rating Curve= 0 ,0
Exp/Cntr=0.3,0.1

Type RM Length L Ch R = 1 ,349.7   ,194.6,194,193.4
XS GIS Cut Line= 4
     1820627.635      133986.264     1820420.935      133934.531
     1820274.035       134070.55     1820245.921      134134.587
#Sta/Elev= 30
     9.7 1501.86    29.1 1493.98    38.7  1490.9    48.4 1489.02    67.8 1487.17
    77.5 1485.59   164.6 1468.68     184 1465.15   203.4 1461.93   223.1 1459.25
   233.1 1458.26   243.1  1457.7   283.1 1457.25   293.2 1456.48   303.2 1455.23
   313.2 1454.65   318.2 1454.64  323.21 1454.53   328.2 1454.84   333.2 1455.05
   343.2 1456.45   353.2 1458.18   373.2 1460.74   393.3 1462.69   413.3 1463.87
   433.3 1466.13   443.3 1467.59   453.2 1469.33   463.2 1471.32   483.2 1475.74
#Mann= 3 , 0 , 0
     9.7     .06       0   318.2    .045       0   328.2     .06       0
Bank Sta=318.2,328.2
XS Rating Curve= 0 ,0
Exp/Cntr=0.3,0.1

Type RM Length L Ch R = 1 ,155.7   ,118,116.9,115.8
XS GIS Cut Line= 4
     1820436.699      133670.159     1820276.528      133800.379
     1820212.608       133863.52     1820115.498      133959.446
#Sta/Elev= 27
     9.8 1449.18    29.5 1449.23    39.3 1449.13    68.8 1448.45    78.6 1448.36
    98.3 1448.44   127.8 1448.85   157.3 1449.05   176.9 1449.04   196.6 1448.86
   216.4 1448.51   236.4 1447.93   246.4 1447.56   266.3 1446.69   276.3 1446.07
   286.3 1445.31   291.3 1445.23   296.3 1445.15   301.3 1445.64     306 1446.09
   325.5 1449.18   335.3 1450.46     345 1451.63   354.8 1452.69   364.5 1453.45
   374.3 1453.67   432.8 1453.61
#Mann= 3 , 0 , 0
       0     .06       0   291.3    .045       0   301.3     .06       0
Bank Sta=291.3,301.3
XS Rating Curve= 0 ,0
Exp/Cntr=0.3,0.1