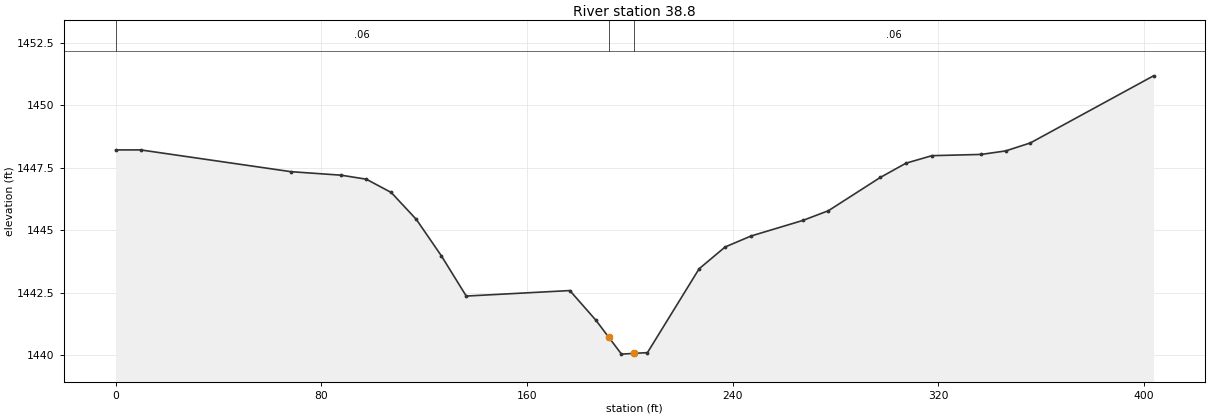
HEC-RAS study Harmon Branch A.prj: Harmon Branch A

--- Harmon Branch A.g01 (geometry) --- (continued)

Type RM Length L Ch R = 1 ,38.8    ,39.5,38.8,38
XS GIS Cut Line= 4
     1820303.537       133737.93     1820167.107      133739.738
     1820045.281      133873.824     1820065.435      133957.624
#Sta/Elev= 27
       0 1448.21     9.7 1448.21    68.2 1447.34    87.7  1447.2    97.5 1447.04
   107.2 1446.51     117 1445.43   126.7 1443.98   136.4 1442.37   176.7 1442.59
   186.8 1441.41   191.8 1440.73   196.8 1440.05   201.8 1440.08   206.9 1440.11
     227 1443.46   237.1 1444.33   247.2 1444.77   267.3 1445.39   277.3 1445.78
   297.5 1447.11   307.5 1447.68   317.6 1447.98   336.8 1448.03   346.3 1448.17
   355.9 1448.49   403.8 1451.17
#Mann= 3 , 0 , 0
       0     .06       0   191.8    .045       0   201.8     .06       0
Bank Sta=191.8,201.8
XS Rating Curve= 0 ,0
Exp/Cntr=0.3,0.1

Chan Stop Cuts=-1
Use User Specified Reach Order=0